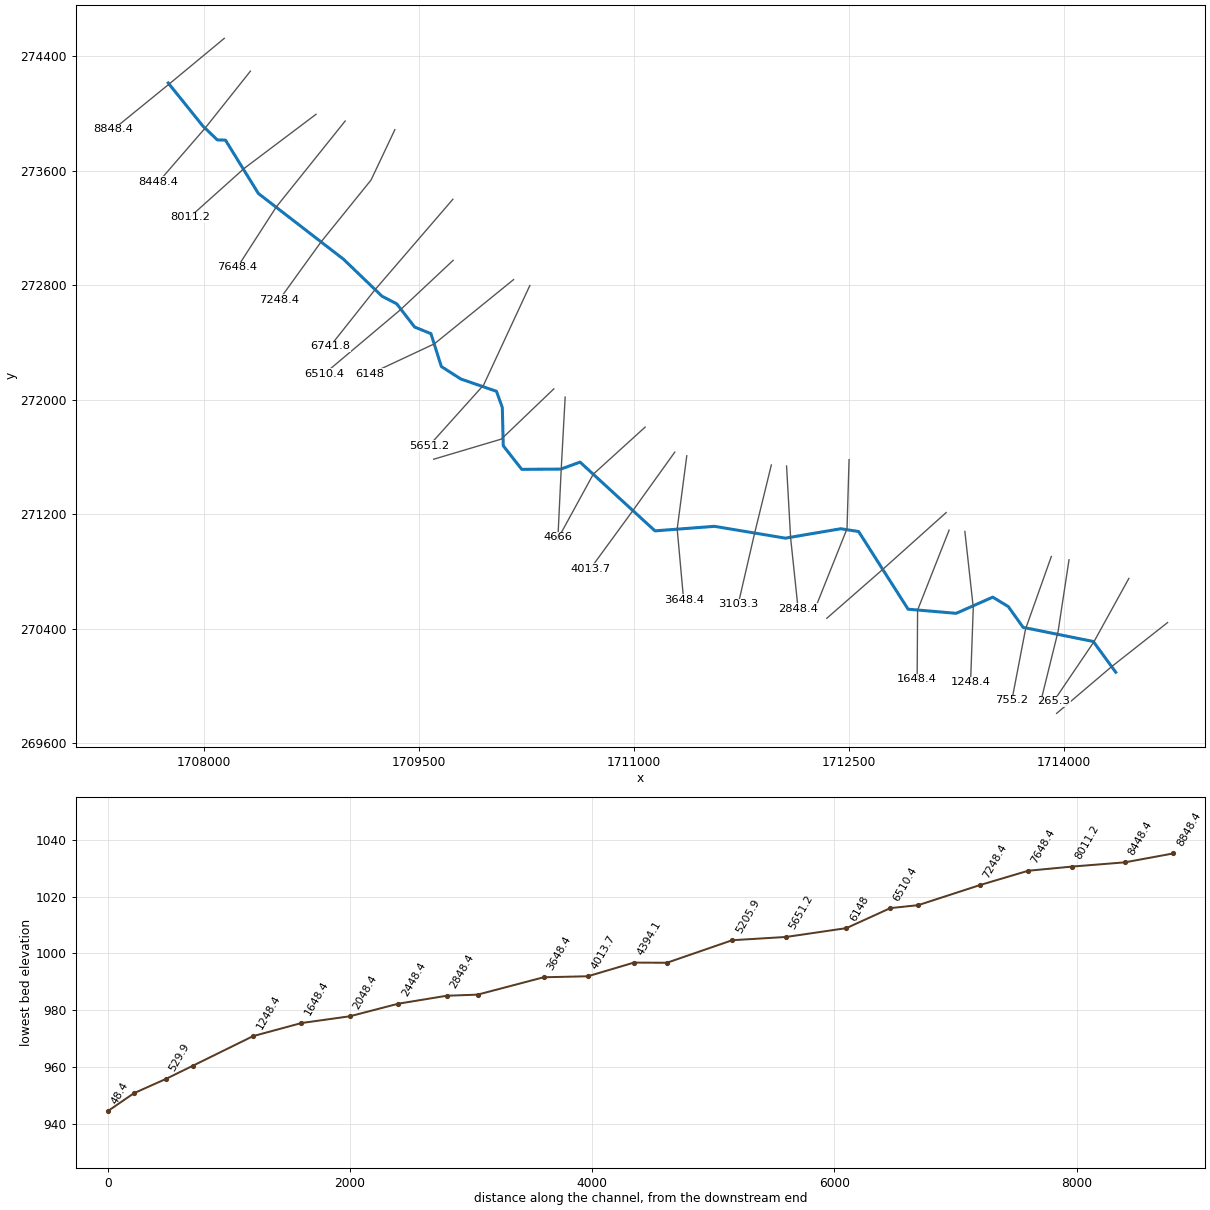
--- CoburnsCr.prj (project) ---

Proj Title=CoburnsCr
Current Plan=p01
Geom File=g01
Flow File=f01
Plan File=p01
DSS Export Rating Curves=0
DSS Export Rating Curve Sorted=0
DSS Export Volume Flow Curves=0
DXF OffsetX=0
DXF OffsetY=0
DXF ScaleX=0
DXF ScaleY=0

--- CoburnsCr.p01 (plan) ---

Plan Title=Floodplain
Program Version=4.00
Geom File=g01
Flow File=f01
K Sum by GR=0
Std Step Tol=0.01
Critical Tol=0.01
Num of Std Step Trials=20
Max Error Tol=0.3
Flow Tol Ratio=0.001
Split Flow NTrial=30
Split Flow Tol=0.02
Split Flow Ratio=0.02
Log Output Level=0
Friction Slope Method=1
Unsteady Friction Slope Method=2
Unsteady Bridges Friction Slope Method=1
Global Log Level=0
CheckData=False
Run HTab=0
Run UNet=0
Run PostProcess=0
UNET Theta=0
UNET Theta Warmup=0
UNET ZTol=0
UNET ZSATol=0
UNET MxIter=0
UNET MaxInSteps=0
UNET DtIC=0
UNET DtMin=0
UNET MaxCRTS=0
UNET WFStab=0
UNET SFStab=0
UNET WFX=0
UNET SFX=0
UNET DSS MLevel=0
UNET DZMax Abort=0
UNET Convert EG Bridges=0
UNET Use Existing IB Tables=0
UNET Froude Limit=0
UNET Froude Power=0
Write IC File=0
Echo Input=False
Echo Output=False
Write Detailed=0

--- CoburnsCr.f01 (steady flow) ---

Flow Title=NFF Regression Equation
Program Version=4.00
Number of Profiles=1
Profile Names=P100yr
River Rch & RM=CoburnsCr,Main      ,8848.4
780.4385
River Rch & RM=CoburnsCr,Main      ,6741.8
820.4076
River Rch & RM=CoburnsCr,Main      ,6510.4
922.2518
River Rch & RM=CoburnsCr,Main      ,5651.2
968.6223
River Rch & RM=CoburnsCr,Main      ,3648.4
1040.488
River Rch & RM=CoburnsCr,Main      ,265.3
1153.284
River Rch & RM=CoburnsCr,Main      ,48.4
1270.683
Boundary for River Rch & Prof#=CoburnsCr,Main      ,1
Up Type=0
Dn Type=3
Dn Slope=0.011528

--- CoburnsCr.g01 (geometry) ---

Geom Title=USGS 3m DEM
Program Version=4.00

River Reach=CoburnsCr     ,Main
Reach XY= 30
     1707751.112      274213.462     1707992.382      273913.223
     1708093.689      273815.593     1708150.712      273813.864
     1708380.103      273441.048     1708973.278      272982.023
     1709242.905      272722.668     1709345.395      272669.668
     1709470.066      272507.487     1709584.037      272461.132
     1709656.518      272231.371     1709792.472      272144.107
     1710041.235      272058.109     1710081.912      271944.427
     1710088.424      271677.399     1710217.477      271512.487
     1710490.543      271514.469     1710624.132      271563.167
     1711146.982      271082.545     1711561.516      271114.224
     1712056.240      271031.577     1712442.812      271097.357
     1712567.538      271077.797     1712912.433      270535.042
     1713247.781      270506.151     1713503.206      270619.076
     1713611.214      270553.692     1713715.268      270407.844
     1714204.409      270309.322     1714361.119      270094.374

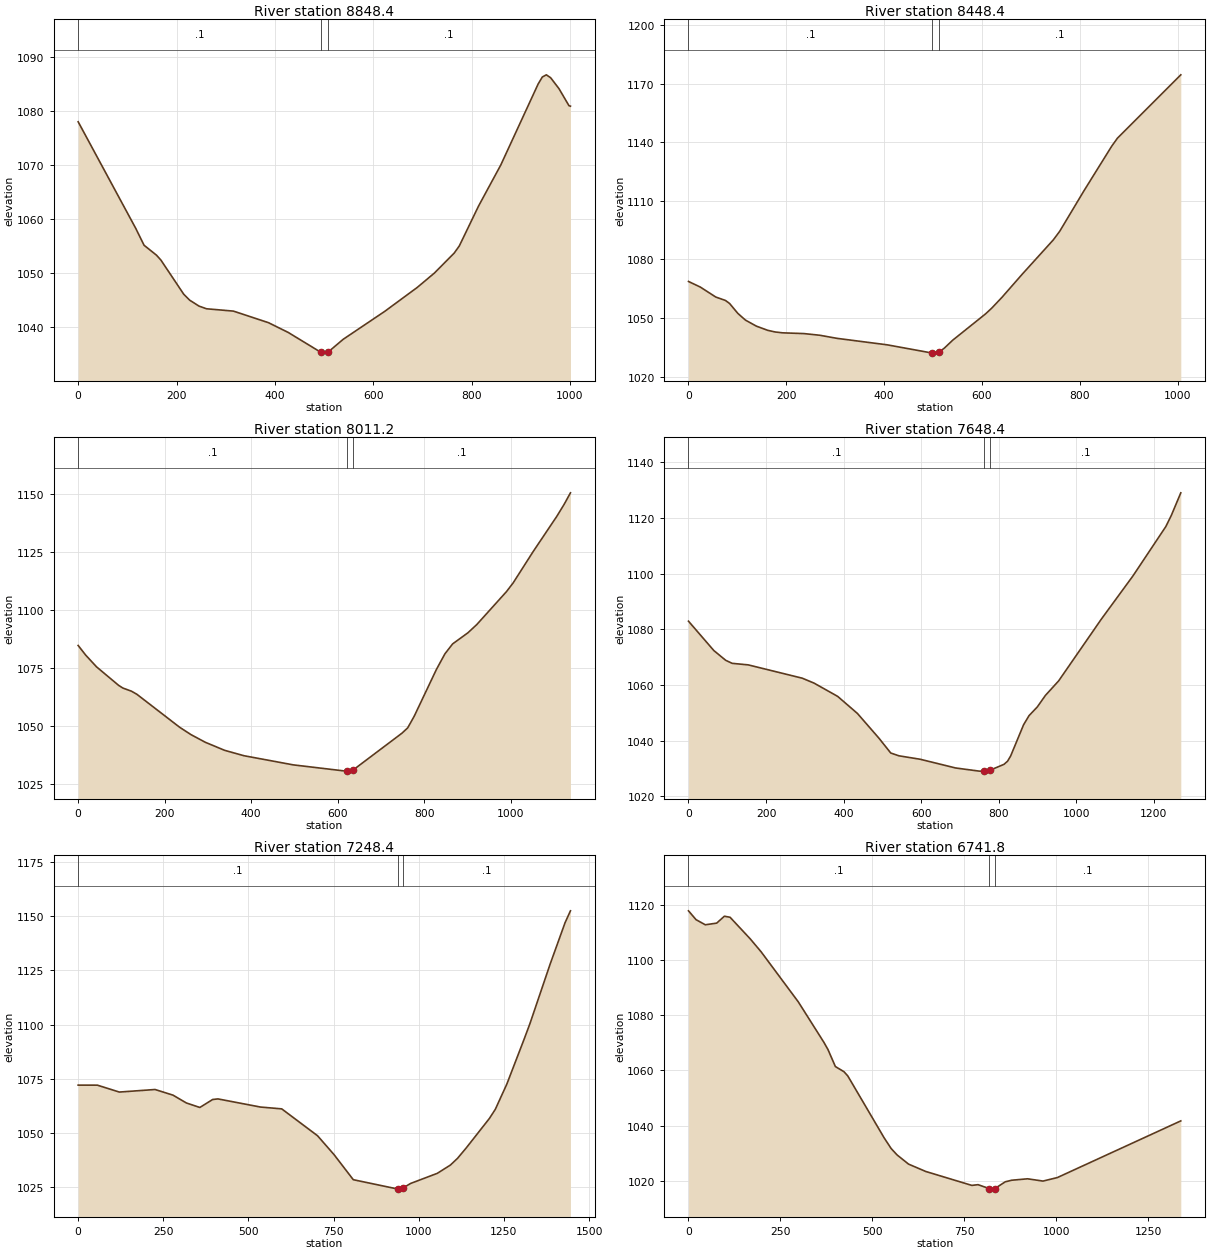
Type RM Length L Ch R = 1 ,8848.4,395.409,400,403.839
XS GIS Cut Line= 3
     1708142.559      274525.495     1707757.501      274205.768
     1707369.449      273889.631
#Sta/Elev= 30
       0 1077.97   117.2 1058.24   134.0 1055.14   159.3 1053.30   168.4 1052.38
   214.7 1046.08   226.8 1044.98   245.6 1043.89   261.0 1043.39   315.7 1042.96
   387.0 1040.82   427.2 1039.01     493 1035.37   496.6 1035.19     508 1035.37
   539.1 1037.76   623.2 1042.90   689.5 1047.34   724.4 1050.00   764.7 1053.70
   775.1 1055.03   814.1 1062.38   859.5 1070.01   935.4 1084.97   943.8 1086.25
   952.0 1086.65   960.7 1086.11   977.6 1084.10   997.9 1080.96  1001.0 1080.85
#Mann= 3 , 0 , 0
       0     0.1       0     493   0.045       0     508     0.1       0
Bank Sta=     493,     508
Exp/Cntr=0.3,0.1

Type RM Length L Ch R = 1 ,8448.4,443.394,437.235,429.389
XS GIS Cut Line= 3
     1708324.799      274296.313     1708010.663      273900.254
     1707683.131      273521.018
#Sta/Elev= 30
       0 1068.73    24.1 1065.88    55.8 1060.76    75.6 1059.01    84.0 1057.47
   100.9 1052.39   116.4 1048.97   138.8 1045.86   161.9 1043.73   177.0 1042.89
   192.2 1042.44   236.2 1042.05   267.9 1041.22   303.8 1039.61   406.2 1036.30
     498 1032.10   501.8 1032.05     513 1032.68   523.4 1034.68   540.2 1038.66
   607.6 1052.18   620.4 1055.17   641.3 1060.71   683.1 1072.65   745.9 1090.01
   759.1 1094.45   808.6 1115.15   865.2 1137.92   877.0 1142.07  1006.6 1174.51
#Mann= 3 , 0 , 0
       0     0.1       0     498   0.045       0     513     0.1       0
Bank Sta=     498,     513
Exp/Cntr=0.3,0.1

Type RM Length L Ch R = 1 ,8011.2,357.019,362.765,368.813
XS GIS Cut Line= 3
     1708782.116      273994.284     1708280.870      273616.055
     1707901.066      273275.068
#Sta/Elev= 30
       0 1084.72    17.2 1080.61    42.6 1075.48    93.4 1067.55   103.3 1066.37
   123.1 1065.02   135.8 1063.67   234.7 1049.46   261.0 1046.27   294.2 1042.97
   338.8 1039.51   383.4 1037.19   497.6 1033.24   619.0 1030.55   620.7 1030.55
   635.7 1031.03   748.6 1046.89   762.0 1049.21   777.0 1054.21   828.4 1074.39
   848.1 1081.13   865.8 1085.38   901.4 1090.21   921.8 1093.75   990.2 1107.89
  1005.8 1111.69  1051.7 1125.09  1106.7 1140.37  1123.5 1145.49  1138.3 1150.51
#Mann= 3 , 0 , 0
       0     0.1       0   620.7   0.045       0   635.7     0.1       0
Bank Sta=   620.7,   635.7
Exp/Cntr=0.3,0.1

Type RM Length L Ch R = 1 ,7648.4,399.978,400,398.907
XS GIS Cut Line= 3
     1708985.679      273947.519     1708504.828      273346.594
     1708234.463      272926.087
#Sta/Elev= 30
       0 1082.96    65.4 1072.40    95.9 1068.91   112.6 1067.81   154.0 1067.26
   293.5 1062.47   323.9 1060.70   384.8 1055.93   435.7 1049.80   491.2 1040.91
   521.6 1035.59   542.5 1034.59   597.7 1033.34   688.9 1030.21   749.7 1029.08
   762.1 1029.08   777.1 1029.37   813.6 1031.52   822.9 1032.65   830.8 1034.52
   864.1 1045.72   878.2 1049.01   899.5 1052.14   920.5 1056.29   954.6 1061.51
  1064.4 1083.64  1146.4 1099.26  1231.0 1116.96  1245.2 1120.98  1269.6 1129.08
#Mann= 3 , 0 , 0
       0     0.1       0   762.1   0.045       0   777.1     0.1       0
Bank Sta=   762.1,   777.1
Exp/Cntr=0.3,0.1

Type RM Length L Ch R = 1 ,7248.4,507.356,506.633,505.087
XS GIS Cut Line= 4
     1709332.288      273887.001     1709166.474      273535.505
     1708817.198      273102.074     1708524.930      272696.283
#Sta/Elev= 30
       0 1072.02    56.4 1072.01   120.9 1068.82   225.8 1070.00   278.4 1067.40
   317.8 1063.78   357.2 1061.71   395.0 1065.39   410.5 1065.66   535.0 1061.91
   597.7 1061.06   702.8 1048.66   751.1 1039.97   807.8 1028.36   937.8 1024.07
   940.3 1024.01   952.8 1024.42   975.9 1026.62  1054.4 1031.30  1093.0 1035.13
  1114.0 1038.25  1139.5 1043.05  1207.5 1056.66  1224.7 1060.83  1258.6 1072.51
  1309.6 1093.33  1326.6 1100.50  1385.6 1127.84  1429.5 1146.99  1445.4 1152.49
#Mann= 3 , 0 , 0
       0     0.1       0   937.8   0.045       0   952.8     0.1       0
Bank Sta=   937.8,   952.8
Exp/Cntr=0.3,0.1

Type RM Length L Ch R = 1 ,6741.8,233.864,231.44,228.158
XS GIS Cut Line= 3
     1709737.011      273400.539     1709190.868      272764.688
     1708880.317      272372.272
#Sta/Elev= 30
       0 1117.81    20.6 1114.60    45.8 1112.75    76.7 1113.36    97.6 1115.86
   113.1 1115.47   167.8 1107.66   197.4 1102.98   298.4 1084.86   368.2 1070.16
   379.3 1067.54   399.4 1061.39   422.9 1059.51   433.1 1058.00   532.2 1035.51
   551.0 1031.70   567.1 1029.38   598.4 1026.04   645.3 1023.37   770.5 1018.33
   787.3 1018.59   817.6 1017.20   823.8 1016.98   832.6 1017.15   861.3 1019.63
   878.7 1020.20   921.8 1020.72   964.0 1019.90  1003.0 1021.17  1338.6 1041.70
#Mann= 3 , 0 , 0
       0     0.1       0   817.6   0.045       0   832.6     0.1       0
Bank Sta=   817.6,   832.6
Exp/Cntr=0.3,0.1

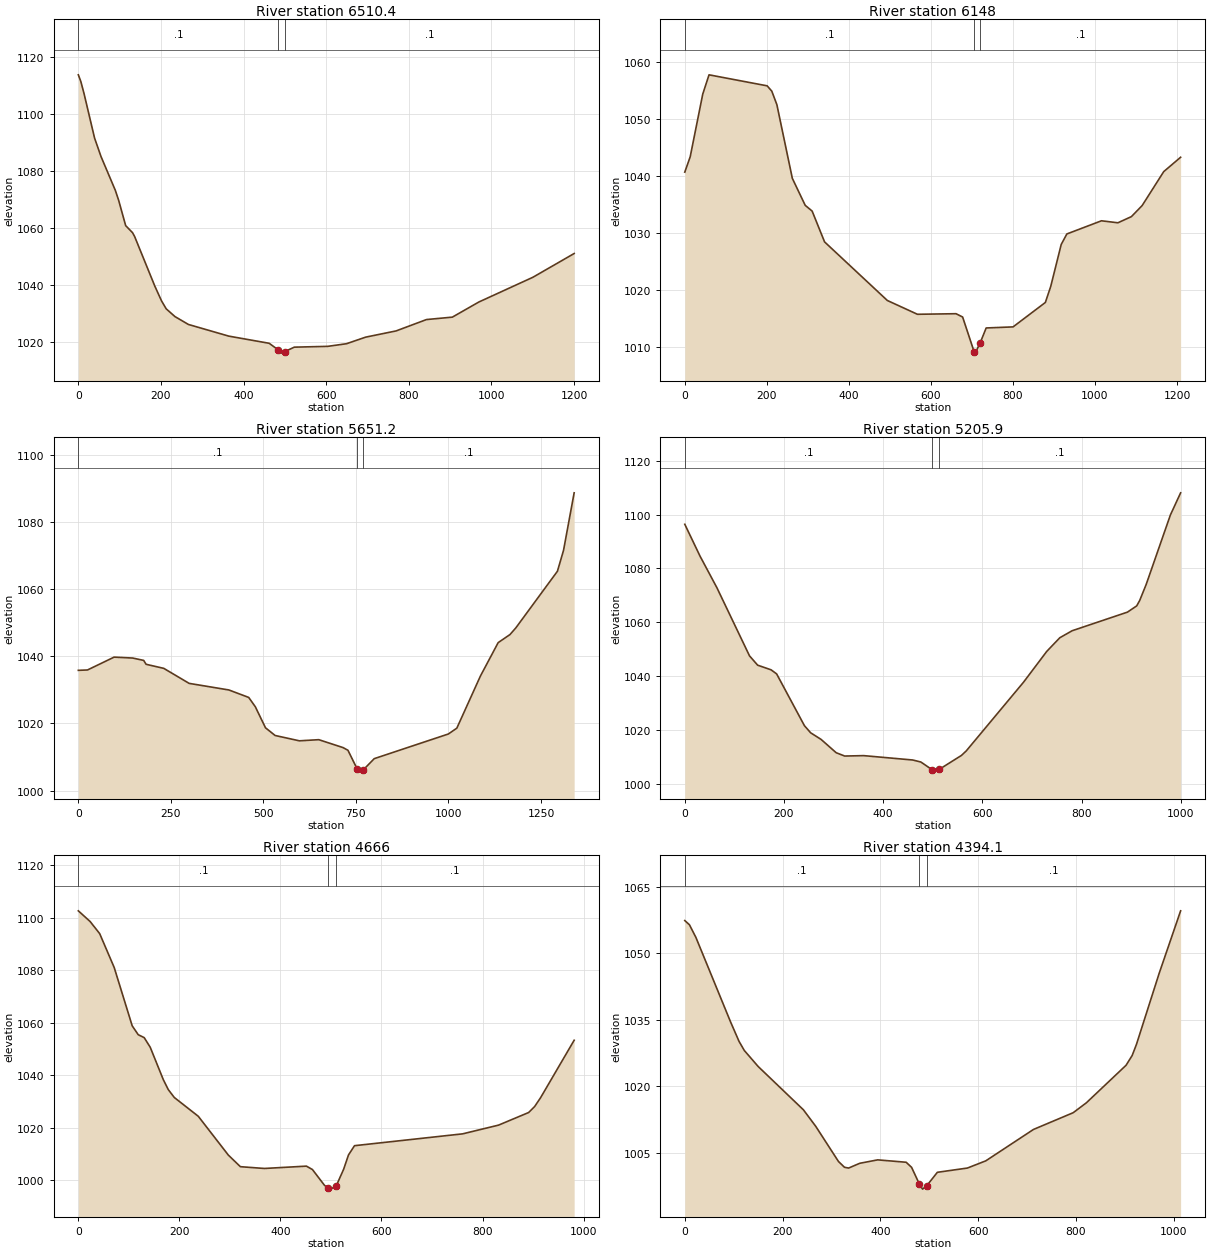
Type RM Length L Ch R = 1 ,6510.4,363.667,362.385,355.398
XS GIS Cut Line= 3
     1709738.958      272973.497     1709370.151      272627.307
     1708839.396      272179.337
#Sta/Elev= 30
       0 1113.82     6.1 1111.46    13.8 1107.23    39.3 1091.58    54.9 1085.08
    89.4 1073.25    97.8 1069.59   114.6 1060.78   131.3 1058.28   136.3 1056.94
   185.2 1039.49   201.5 1034.28   212.8 1031.49   234.0 1028.77   266.6 1026.00
   364.3 1021.90   462.0 1019.38   484.3 1017.04   491.5 1015.92   499.3 1016.44
   523.0 1018.02   603.6 1018.30   649.3 1019.23   695.6 1021.54   769.3 1023.73
   842.9 1027.73   905.5 1028.58   969.5 1033.89  1100.6 1042.61  1200.4 1050.96
#Mann= 3 , 0 , 0
       0     0.1       0   484.3   0.045       0   499.3     0.1       0
Bank Sta=   484.3,   499.3
Exp/Cntr=0.3,0.1

Type RM Length L Ch R = 1 ,6148,486.681,496.817,507.592
XS GIS Cut Line= 3
     1710160.297      272838.923     1709608.158      272390.052
     1709157.969      272178.723
#Sta/Elev= 30
       0 1040.61    13.2 1043.31    43.8 1054.30    59.1 1057.67   200.8 1055.74
   212.1 1054.81   224.5 1052.44   262.2 1039.52   293.6 1034.79   310.5 1033.78
   340.8 1028.38   493.8 1018.11   567.2 1015.69   661.3 1015.79   677.4 1015.21
   705.3 1009.15   708.0 1008.88   720.3 1010.70   734.8 1013.29   800.4 1013.48
   879.1 1017.76   892.2 1020.57   917.7 1027.92   931.5 1029.77  1015.9 1032.08
  1056.0 1031.73  1088.9 1032.81  1115.1 1034.75  1167.7 1040.70  1208.9 1043.22
#Mann= 3 , 0 , 0
       0     0.1       0   705.3   0.045       0   720.3     0.1       0
Bank Sta=   705.3,   720.3
Exp/Cntr=0.3,0.1

Type RM Length L Ch R = 1 ,5651.2,450.589,445.256,431.804
XS GIS Cut Line= 3
     1710273.827      272797.494     1709951.231      272101.692
     1709568.862      271675.309
#Sta/Elev= 30
       0 1035.78    24.8 1035.89    96.6 1039.71   146.8 1039.44   176.6 1038.74
   183.1 1037.58   230.9 1036.37   299.4 1031.90   406.7 1029.94   460.3 1027.72
   478.2 1024.95   505.7 1018.68   531.7 1016.39   597.3 1014.80   649.7 1015.14
   715.1 1012.79   728.5 1011.99   753.7 1006.36   766.9 1005.78   768.7 1006.01
   799.5 1009.49   999.9 1016.84  1022.7 1018.57  1086.5 1034.10  1134.4 1044.03
  1166.3 1046.43  1182.2 1048.43  1294.5 1065.28  1311.0 1071.50  1339.7 1088.62
#Mann= 3 , 0 , 0
       0     0.1       0   753.7   0.045       0   768.7     0.1       0
Bank Sta=   753.7,   768.7
Exp/Cntr=0.3,0.1

Type RM Length L Ch R = 1 ,5205.9,527.862,539.867,567.215
XS GIS Cut Line= 3
     1710441.151      272075.071     1710075.263      271724.033
     1709603.014      271583.352
#Sta/Elev= 30
       0 1096.42    30.8 1084.55    64.7 1072.85   130.5 1047.49   146.9 1044.03
   174.0 1042.30   185.2 1040.78   241.2 1021.54   253.8 1018.88   274.8 1016.43
   305.2 1011.48   322.4 1010.24   360.8 1010.39   459.5 1008.77   476.0 1008.02
   498.5 1005.18   508.4 1004.63   513.5 1005.33   558.0 1010.49   567.6 1012.16
   683.0 1037.69   729.9 1049.16   756.2 1054.23   781.0 1056.83   892.5 1063.75
   911.2 1066.07   917.3 1068.10   930.3 1074.02   979.2 1099.89   999.8 1108.12
#Mann= 3 , 0 , 0
       0     0.1       0   498.5   0.045       0   513.5     0.1       0
Bank Sta=   498.5,   513.5
Exp/Cntr=0.3,0.1

Type RM Length L Ch R = 1 ,4666,287.651,271.892,261.672
XS GIS Cut Line= 3
     1710520.363      272017.723     1710492.804      271514.774
     1710469.871      271037.702
#Sta/Elev= 30
       0 1102.59    23.4 1098.51    42.3 1093.90    71.0 1081.02   106.6 1058.84
   118.5 1055.46   130.4 1054.33   142.3 1050.67   168.1 1038.39   178.0 1034.57
   189.9 1031.57   237.4 1024.41   296.9 1009.64   320.7 1005.23   368.2 1004.55
   451.4 1005.44   463.3 1004.15   487.1  998.16     495  996.94   499.0  996.69
     510  997.74   525.1 1004.27   534.7 1009.70   546.6 1013.22   760.5 1017.72
   831.8 1021.05   891.3 1025.85   903.1 1028.12   915.0 1031.52   981.3 1053.34
#Mann= 3 , 0 , 0
       0     0.1       0     495   0.045       0     510     0.1       0
Bank Sta=     495,     510
Exp/Cntr=0.3,0.1

Type RM Length L Ch R = 1 ,4394.1,375.578,380.417,377.807
XS GIS Cut Line= 3
     1711078.235      271807.778     1710716.356      271478.755
     1710464.823      271017.824
#Sta/Elev= 30
       0 1057.42     9.5 1056.47    22.7 1053.62    93.3 1034.61   110.9 1030.14
   121.8 1028.06   150.2 1024.44   242.7 1014.66   267.9 1010.93   314.3 1003.00
   326.7 1001.68   335.1 1001.51   358.0 1002.59   394.6 1003.36   452.8 1002.82
   463.9 1001.67     480  997.85   486.4  996.75     495  997.53   516.6 1000.55
   578.0 1001.51   615.7 1003.14   713.2 1010.23   794.4 1014.01   821.4 1016.25
   902.6 1024.73   915.1 1026.94   923.8 1029.43   970.2 1045.46  1014.2 1059.62
#Mann= 3 , 0 , 0
       0     0.1       0     480   0.045       0     495     0.1       0
Bank Sta=     480,     495
Exp/Cntr=0.3,0.1

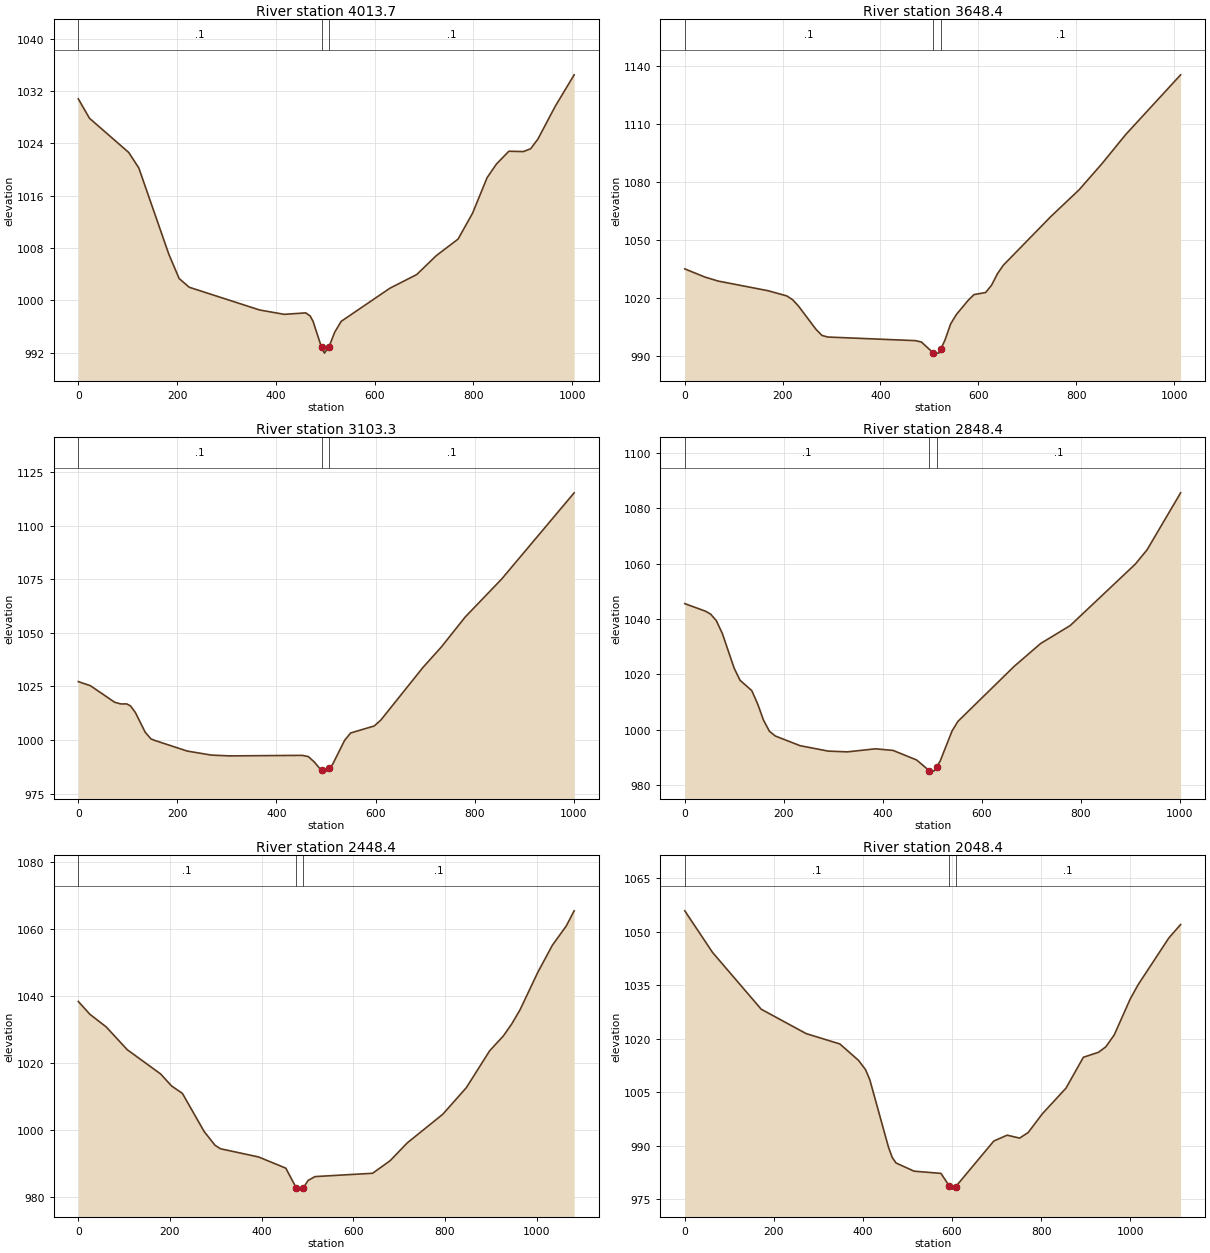
Type RM Length L Ch R = 1 ,4013.7,353.452,365.294,382.391
XS GIS Cut Line= 3
     1711284.968      271632.841     1710993.864      271225.942
     1710696.786      270818.689
#Sta/Elev= 30
       0 1030.80    22.6 1027.84   102.1 1022.61   122.5 1020.24   183.2 1007.07
   204.1 1003.35   224.5 1002.01   367.3  998.53   416.8  997.87   460.6  998.09
   469.4  997.62   475.2  996.82   492.5  992.82   498.3  991.94   507.5  992.88
   519.1  995.14   532.3  996.80   630.9 1001.86   685.2 1003.95   724.8 1006.84
   768.9 1009.37   798.3 1013.33   827.7 1018.76   846.7 1020.85   871.8 1022.80
   901.2 1022.75   915.9 1023.18   930.6 1024.66   965.6 1029.66  1004.0 1034.48
#Mann= 3 , 0 , 0
       0     0.1       0   492.5   0.045       0   507.5     0.1       0
Bank Sta=   492.5,   507.5
Exp/Cntr=0.3,0.1

Type RM Length L Ch R = 1 ,3648.4,547.57,545.177,538.014
XS GIS Cut Line= 3
     1711368.750      271607.313     1711301.777      271095.950
     1711346.709      270600.169
#Sta/Elev= 30
       0 1035.12    40.7 1030.93    68.4 1028.81   170.0 1023.84   208.3 1021.16
   220.3 1019.21   232.3 1015.93   268.2 1003.87   280.2 1000.74   292.2  999.90
   471.8  998.03   483.7  997.31   508.2  991.62   514.5  991.58   519.6  991.62
   523.2  993.71   531.6  998.18   543.5 1006.73   555.4 1011.64   579.3 1018.88
   591.2 1021.83   615.0 1022.91   626.9 1026.64   638.9 1032.52   650.8 1036.93
   748.4 1062.22   805.8 1075.93   853.3 1089.66   901.1 1104.50  1013.5 1135.40
#Mann= 3 , 0 , 0
       0     0.1       0   508.2   0.045       0   523.2     0.1       0
Bank Sta=   508.2,   523.2
Exp/Cntr=0.3,0.1

Type RM Length L Ch R = 1 ,3103.3,248.149,254.823,262.312
XS GIS Cut Line= 3
     1711958.562      271543.142     1711839.751      271056.895
     1711727.309      270569.199
#Sta/Elev= 30
       0 1027.25    24.4 1025.34    73.3 1017.62    85.8 1016.83    97.7 1016.84
   105.4 1015.89   115.2 1012.83   134.9 1003.67   146.6 1000.51   154.5  999.78
   219.9  994.83   268.8  992.95   305.5  992.58   452.1  992.83   464.4  992.25
   476.6  989.68   488.5  986.38   491.8  986.10   500.6  985.47   506.8  986.75
   513.2  988.57   537.6  999.84   549.8 1003.28   597.3 1006.54   610.7 1009.30
   696.0 1033.93   732.5 1043.30   781.3 1057.47   854.4 1075.06  1001.0 1115.36
#Mann= 3 , 0 , 0
       0     0.1       0   491.8   0.045       0   506.8     0.1       0
Bank Sta=   491.8,   506.8
Exp/Cntr=0.3,0.1

Type RM Length L Ch R = 1 ,2848.4,401.966,400,388.619
XS GIS Cut Line= 3
     1712064.799      271535.859     1712092.935      271035.433
     1712145.228      270537.800
#Sta/Elev= 30
       0 1045.58    41.6 1042.87    52.1 1041.81    63.8 1039.41    75.9 1034.76
    99.7 1022.28   111.6 1017.90   135.3 1014.17   147.2 1009.36   159.1 1003.46
   171.0  999.47   182.9  997.76   233.0  994.27   289.9  992.31   328.4  992.04
   385.1  993.14   420.7  992.56   468.3  989.11   493.7  985.28   503.1  985.08
   508.7  986.64   515.9  988.72   539.8  999.56   551.7 1003.04   665.2 1022.90
   718.9 1031.19   778.6 1037.67   909.9 1059.83   933.8 1065.02  1001.6 1085.61
#Mann= 3 , 0 , 0
       0     0.1       0   493.7   0.045       0   508.7     0.1       0
Bank Sta=   493.7,   508.7
Exp/Cntr=0.3,0.1

Type RM Length L Ch R = 1 ,2448.4,418.598,400,389.416
XS GIS Cut Line= 3
     1712500.791      271580.273     1712486.499      271097.630
     1712264.666      270540.933
#Sta/Elev= 30
       0 1038.30    25.2 1034.48    60.8 1030.71   106.7 1023.91   179.6 1016.66
   203.4 1013.09   227.1 1010.86   274.6  999.48   298.4  995.36   310.3  994.33
   393.4  991.88   452.8  988.54   475.4  982.70   488.5  982.28   490.4  982.58
   501.6  984.88   516.4  986.02   642.2  987.01   680.6  990.78   717.5  996.04
   795.6 1004.66   846.7 1012.55   897.8 1023.60   927.7 1028.03   946.0 1031.62
   964.2 1035.87  1002.6 1046.96  1034.6 1055.10  1064.8 1060.82  1082.1 1065.36
#Mann= 3 , 0 , 0
       0     0.1       0   475.4   0.045       0   490.4     0.1       0
Bank Sta=   475.4,   490.4
Exp/Cntr=0.3,0.1

Type RM Length L Ch R = 1 ,2048.4,390.205,400,419.067
XS GIS Cut Line= 3
     1713177.990      271210.414     1712730.914      270809.013
     1712345.368      270471.369
#Sta/Elev= 30
       0 1055.80    62.3 1044.15   171.6 1028.24   272.5 1021.41   348.2 1018.51
   390.1 1013.91   406.0 1011.28   415.5 1008.45   457.5  989.53   465.9  986.69
   474.3  985.17   514.8  982.88   575.2  982.26   593.3  978.83   600.4  977.85
   608.3  978.54   693.8  991.32   723.8  992.96   751.9  992.14   771.1  993.72
   802.7  998.93   856.0 1006.15   894.9 1014.78   928.9 1016.18   945.4 1017.71
   964.2 1021.04  1000.2 1031.13  1018.2 1035.17  1086.8 1048.19  1113.3 1051.97
#Mann= 3 , 0 , 0
       0     0.1       0   593.3   0.045       0   608.3     0.1       0
Bank Sta=   593.3,   608.3
Exp/Cntr=0.3,0.1

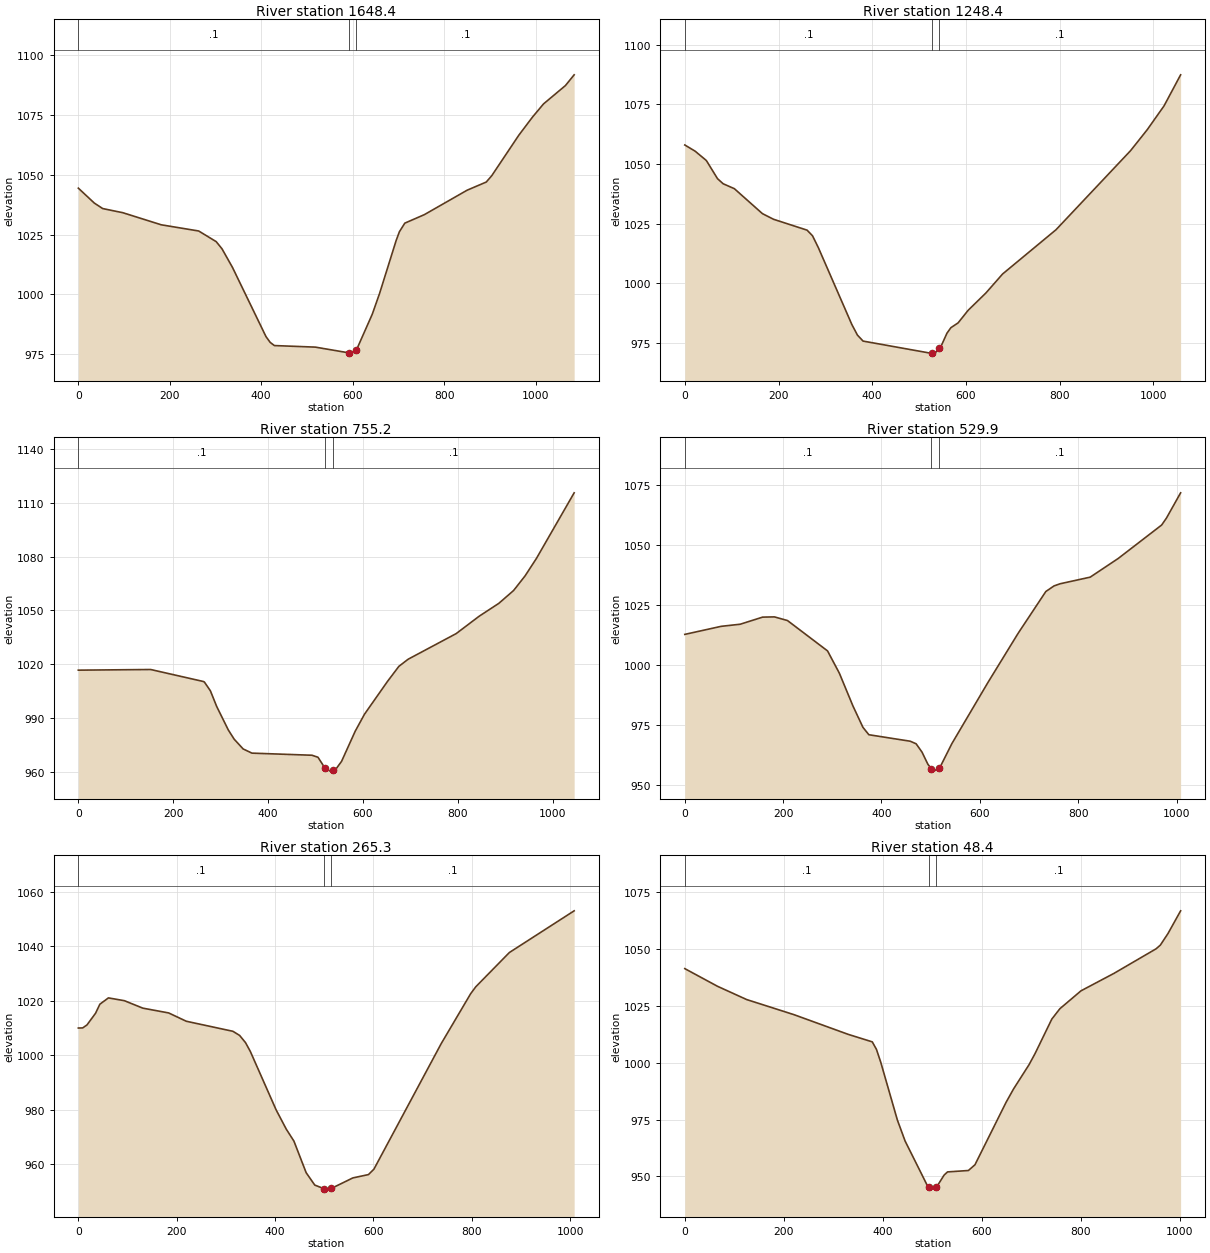
Type RM Length L Ch R = 1 ,1648.4,388.433,400,399.017
XS GIS Cut Line= 3
     1713198.703      271087.623     1712978.839      270528.794
     1712975.716      270045.042
#Sta/Elev= 30
       0 1044.41    35.0 1038.17    53.3 1035.88    97.3 1034.15   181.5 1029.09
   263.2 1026.51   301.5 1022.06   314.2 1019.06   337.1 1011.29   410.4  982.37
   419.5  979.97   428.7  978.63   518.3  977.98     593  975.54   594.9  975.47
     608  976.70   642.8  991.73   658.9 1000.48   694.8 1022.40   702.1 1026.18
   714.0 1029.79   756.6 1033.33   850.1 1043.54   892.1 1046.97   904.0 1049.59
   963.3 1066.54   993.5 1074.19  1017.4 1079.63  1065.2 1087.28  1084.3 1091.77
#Mann= 3 , 0 , 0
       0     0.1       0     593   0.045       0     608     0.1       0
Bank Sta=     593,     608
Exp/Cntr=0.3,0.1

Type RM Length L Ch R = 1 ,1248.4,504.372,493.279,487.754
XS GIS Cut Line= 3
     1713308.629      271078.436     1713367.294      270546.495
     1713348.321      270023.754
#Sta/Elev= 30
       0 1057.97    22.1 1055.37    46.0 1051.47    69.9 1043.85    81.9 1041.74
   105.8 1039.68   165.7 1029.23   189.4 1026.87   261.0 1022.32   272.6 1019.97
   284.9 1015.07   356.6  982.81   368.5  978.40   380.5  975.89   523.8  970.85
   527.7  971.01   535.2  971.05   542.7  972.97   547.6  973.99   559.5  979.17
   567.9  981.49   583.3  983.50   604.9  988.80   642.7  996.02   678.3 1003.97
   792.4 1022.51   951.6 1055.62   987.1 1064.38  1022.9 1074.33  1058.3 1087.33
#Mann= 3 , 0 , 0
       0     0.1       0   527.7   0.045       0   542.7     0.1       0
Bank Sta=   527.7,   542.7
Exp/Cntr=0.3,0.1

Type RM Length L Ch R = 1 ,755.2,221.178,225.235,225.533
XS GIS Cut Line= 3
     1713911.776      270903.294     1713731.856      270395.976
     1713636.527      269898.137
#Sta/Elev= 30
       0 1016.72   152.5 1017.08   263.7 1010.40   265.8 1010.08   278.4 1005.22
   291.6  996.54   316.2  983.40   328.6  978.26   347.4  972.85   366.0  970.52
   492.6  969.34   505.2  968.22   517.8  963.03   520.8  962.46   530.4  960.50
   535.8  960.98   543.0  961.65   554.9  965.94   583.6  982.69   603.2  992.18
   651.6 1010.41   675.7 1018.83   695.2 1022.80   796.6 1037.09   845.0 1046.76
   886.3 1053.89   917.5 1061.06   941.7 1069.19   965.9 1079.03  1045.2 1115.46
#Mann= 3 , 0 , 0
       0     0.1       0   520.8   0.045       0   535.8     0.1       0
Bank Sta=   520.8,   535.8
Exp/Cntr=0.3,0.1

Type RM Length L Ch R = 1 ,529.9,272.367,264.62,256.629
XS GIS Cut Line= 3
     1714035.174      270880.351     1713959.128      270380.376
     1713838.758      269892.385
#Sta/Elev= 30
       0 1012.75    74.1 1016.11   112.7 1016.98   158.2 1019.94   182.2 1020.04
   208.8 1018.52   290.3 1005.87   314.3  996.60   342.0  982.91   362.3  974.03
   374.3  970.96   458.4  968.26   470.4  967.19   482.4  963.72   494.4  958.64
   501.6  956.78   506.4  955.80   516.6  956.99   519.0  957.42   543.1  967.25
   616.4  992.70   677.6 1013.12   734.2 1030.61   751.0 1032.95   763.2 1033.83
   824.4 1036.59   881.4 1044.37   969.7 1058.30   979.5 1061.20  1008.3 1071.71
#Mann= 3 , 0 , 0
       0     0.1       0   501.6   0.045       0   516.6     0.1       0
Bank Sta=   501.6,   516.6
Exp/Cntr=0.3,0.1

Type RM Length L Ch R = 1 ,265.3,226.034,216.866,210.557
XS GIS Cut Line= 3
     1714452.635      270750.127     1714208.780      270307.078
     1713927.456      269890.567
#Sta/Elev= 30
       0 1009.93     8.8 1009.97    17.5 1011.05    35.0 1015.35    43.8 1018.68
    61.2 1021.00    93.7 1019.97   131.2 1017.23   183.6 1015.48   219.6 1012.42
   314.4 1008.73   328.0 1007.21   339.9 1004.59   349.7 1001.36   402.2  979.89
   422.8  972.81   438.4  968.41   463.3  956.80   480.8  952.25   499.8  950.91
   507.0  950.76   514.8  951.04   558.3  954.88   590.0  956.10   601.1  958.09
   737.9 1004.19   797.8 1022.53   808.3 1025.09   876.6 1037.67  1008.3 1052.98
#Mann= 3 , 0 , 0
       0     0.1       0   499.8   0.045       0   514.8     0.1       0
Bank Sta=   499.8,   514.8
Exp/Cntr=0.3,0.1

Type RM Length L Ch R = 1 ,48.4,47.613,48.436,48.421
XS GIS Cut Line= 3
     1714722.841      270441.704     1714329.877      270131.379
     1713948.791      269806.751
#Sta/Elev= 30
       0 1041.33    65.8 1033.59   125.0 1027.73   220.3 1021.11   330.0 1012.44
   378.6 1009.14   387.0 1005.86   395.5 1000.35   429.3  974.79   444.9  965.56
   488.5  946.55   493.2  945.42   505.4  944.42   508.2  945.24   523.6  950.58
   530.6  951.99   572.7  952.60   586.0  955.13   648.8  982.57   664.0  988.48
   695.2  999.11   707.5 1004.06   741.2 1019.16   757.5 1023.71   800.1 1031.57
   866.7 1039.24   951.7 1050.03   960.3 1051.65   975.9 1056.79  1001.3 1066.73
#Mann= 3 , 0 , 0
       0     0.1       0   493.2   0.045       0   508.2     0.1       0
Bank Sta=   493.2,   508.2
Exp/Cntr=0.3,0.1